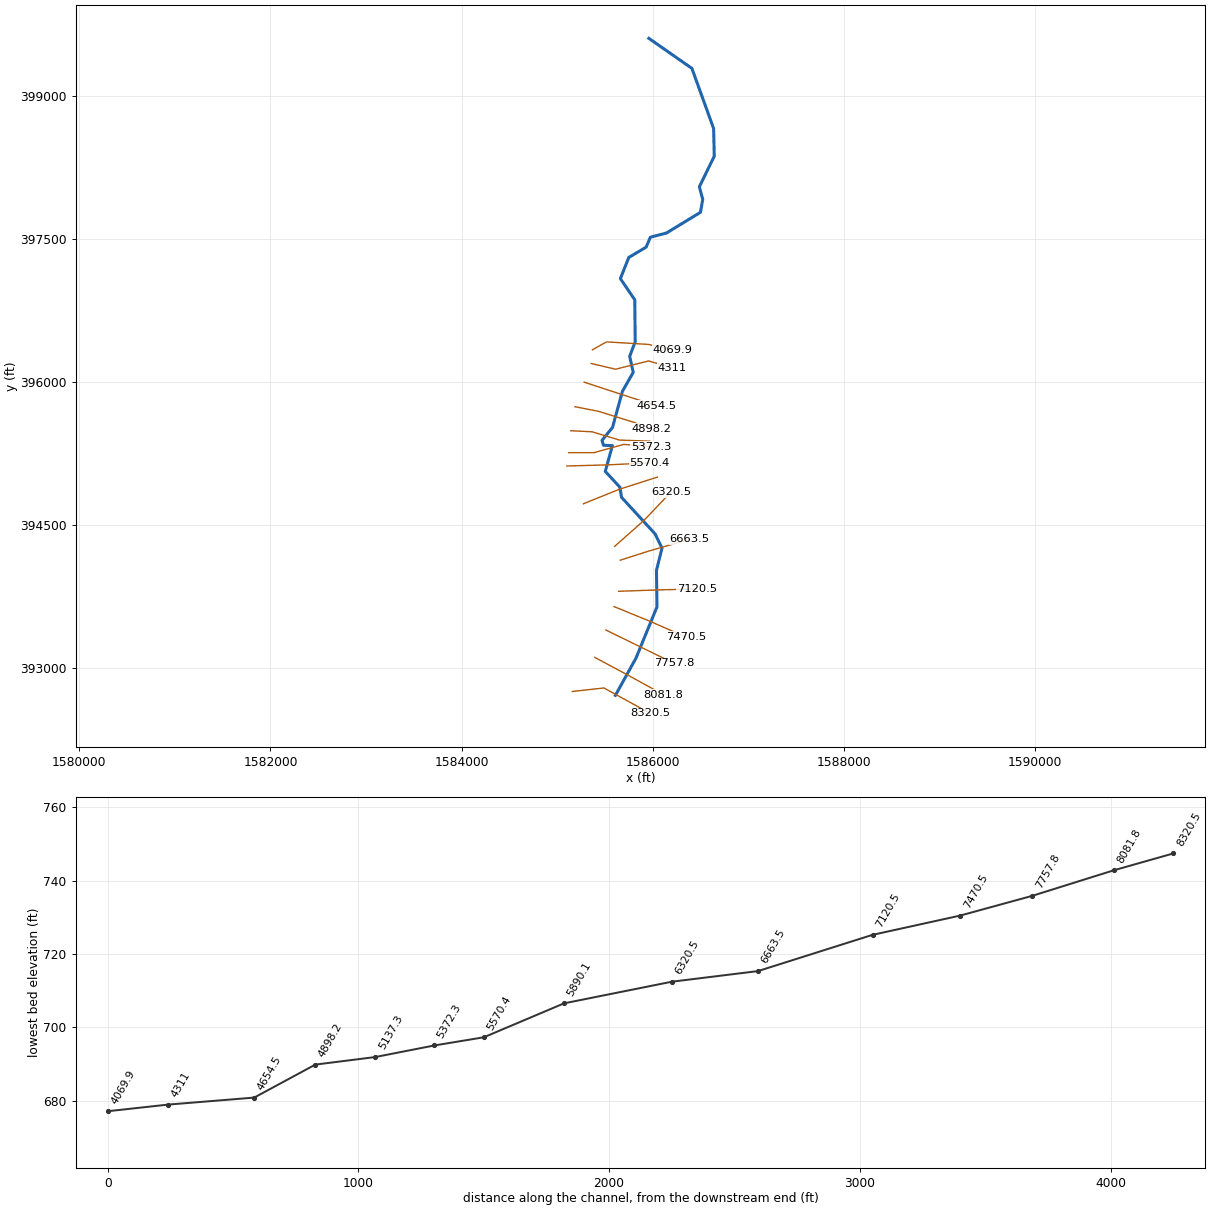
--- BLULICKBR.prj (project) ---

Proj Title=BLULICKBR
Current Plan=p01
Default Exp/Contr=0,0
English Units
Geom File=g01
Flow File=f01
Plan File=p01
BEGIN DESCRIPTION:
END DESCRIPTION:
DSS Export Rating Curves= 0
DSS Export Rating Curve Sorted= 0
DSS Export Volume Flow Curves= 0
DXF OffsetX= 0
DXF OffsetY= 0
DXF ScaleX= 0
DXF ScaleY= 0

--- BLULICKBR.p01 (plan) ---

Plan Title=Floodplain
Program Version=4.00
Geom File=g01
Flow File=f01
K Sum by GR=0
Std Step Tol=0.01
Critical Tol=0.01
Num of Std Step Trials=20
Max Error Tol=0.3
Flow Tol Ratio=0.001
Split Flow NTrial=30
Split Flow Tol=0.02
Split Flow Ratio=0.02
Log Output Level=0
Friction Slope Method=1
Unsteady Friction Slope Method=2
Unsteady Bridges Friction Slope Method=1
Global Log Level=0
CheckData=False
Run HTab=0
Run UNet=0
Run PostProcess=0
UNET Theta=0
UNET Theta Warmup=0
UNET ZTol=0
UNET ZSATol=0
UNET MxIter=0
UNET MaxInSteps=0
UNET DtIC=0
UNET DtMin=0
UNET MaxCRTS=0
UNET WFStab=0
UNET SFStab=0
UNET WFX=0
UNET SFX=0
UNET DSS MLevel=0
UNET DZMax Abort=0
UNET Convert EG Bridges=0
UNET Use Existing IB Tables=0
UNET Froude Limit=0
UNET Froude Power=0
Write IC File=0
Echo Input=False
Echo Output=False
Write Detailed=0

--- BLULICKBR.f01 (steady flow) ---

Flow Title=NFF Regression Equation
Program Version=4.00
Number of Profiles=1
Profile Names=P100yr
River Rch & RM=BLULICKBR,Main      ,8320.5
     311
River Rch & RM=BLULICKBR,Main      ,8081.8
     402
River Rch & RM=BLULICKBR,Main      ,7470.5
     435
River Rch & RM=BLULICKBR,Main      ,5372.3
     479
Boundary for River Rch & Prof#=BLULICKBR,Main      ,1
Up Type=0
Dn Type=3
Dn Slope=0.016663

--- BLULICKBR.g01 (geometry) ---

Geom Title=USGS 10m DEM
Program Version=4.00

River Reach=BLULICKBR       ,Main
Reach XY= 30
     1585609.688      392710.993     1585825.507      393102.132
     1586044.627      393638.304     1586039.442      394020.551
     1586097.437      394255.311     1586024.821      394404.398
     1585673.929      394787.635     1585656.633      394893.927
     1585503.628      395060.104     1585578.197       395329.79
     1585484.681      395333.635     1585469.612      395386.538
     1585579.083      395519.276     1585682.825      395898.494
     1585796.097      396097.906     1585759.097      396266.935
     1585816.952      396417.997     1585812.281      396859.272
     1585661.734      397081.701     1585749.845      397303.574
     1585930.991      397411.292     1585975.966      397515.775
     1586144.662      397560.014     1586499.334      397776.386
     1586523.871      397912.456     1586488.181      398044.064
     1586644.326      398365.276     1586637.634       398655.26
     1586410.108      399286.532     1585959.463      399601.325

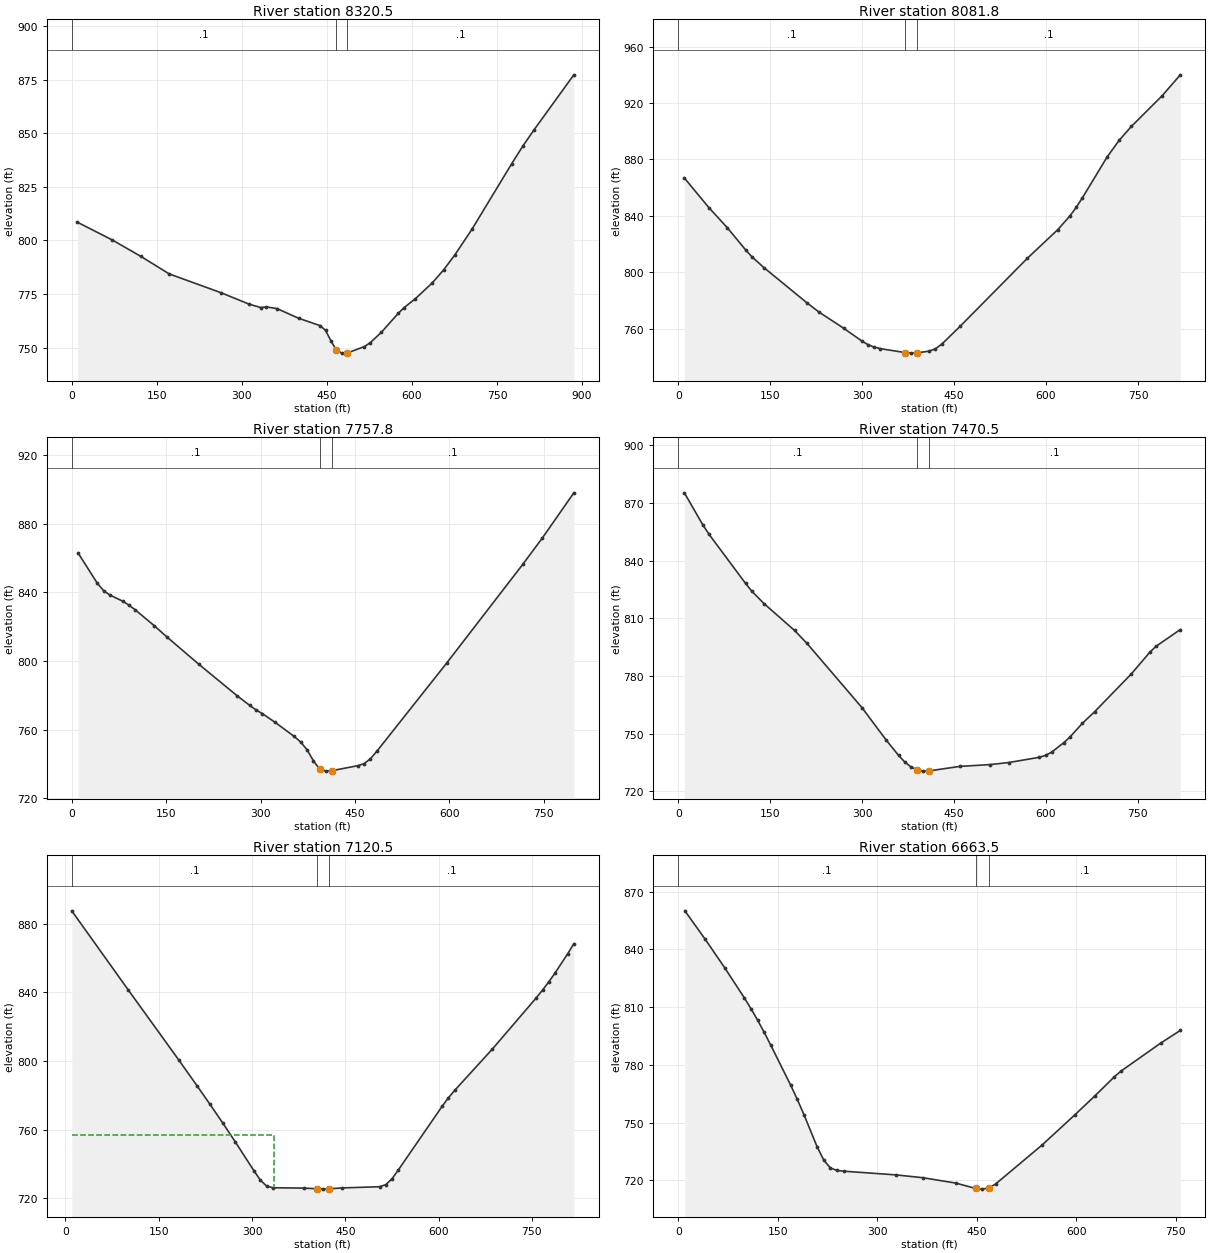
Type RM Length L Ch R = 1 ,8320.5  ,238.5,238.8,239
XS GIS Cut Line= 4
     1585158.191      392751.454     1585489.794       392788.56
     1585614.519      392719.749     1585973.072      392521.937
#Sta/Elev= 30
    10.1   808.5    70.8  800.33   121.3  792.68   171.9   784.4   262.9  775.67
   313.4  770.23   333.7   768.7   343.2  769.02   362.2  768.21   400.1  763.71
   438.1  760.26   447.6  758.05   457.1  753.19   466.1   749.1   476.1  747.44
   486.1  747.51   516.1  750.49   526.1  752.22     546  757.13     576  766.04
     586  768.63     606  772.82   635.9  780.22   655.9  786.27   675.9  793.35
   705.8   805.2   775.8  835.75   795.7   844.1   815.7  851.75   885.6   877.3
#Mann= 3 , 0 , 0
       0      .1       0   466.1    .045       0   486.1      .1       0
Bank Sta=466.1,486.1
XS Rating Curve= 0 ,0
Exp/Cntr=0.3,0.1

Type RM Length L Ch R = 1 ,8081.8  ,323,324,324.9
XS GIS Cut Line= 3
     1585394.174      393109.109     1585754.953      392915.319
     1586113.484      392717.477
#Sta/Elev= 30
      10  866.88    49.9  845.95    79.9  831.72   109.9  815.98   119.9  811.21
   139.8   803.4   209.8   778.5   229.7  771.88   269.7   760.5   299.7  751.34
   309.6  748.83   319.6  747.05   329.6  746.02   369.6  743.23   379.6  742.82
   389.6  742.98   409.5  744.26   419.5   745.9   429.5  749.01   459.5  761.69
   569.3  809.93   619.3  830.37   639.2  840.15   649.2  846.09   659.2  852.77
   699.2  881.49   719.1  893.48   739.1  903.39   789.1  925.03     819  939.97
#Mann= 3 , 0 , 0
       0      .1       0   369.6    .045       0   389.6      .1       0
Bank Sta=369.6,389.6
XS Rating Curve= 0 ,0
Exp/Cntr=0.3,0.1

Type RM Length L Ch R = 1 ,7757.8  ,285.6,287.3,288.6
XS GIS Cut Line= 2
     1585508.993      393396.477     1586225.686      393045.675
#Sta/Elev= 30
    10.1  862.86    40.4  845.36    50.5  840.96    60.6  838.39    80.8  834.84
    90.9  832.52     101  829.73   131.3  820.47   151.5  813.89     202  798.08
   262.6  779.81   282.8  774.15   292.9  771.52     303  769.32   323.2  764.28
   353.5  756.07   363.6  752.88   373.7  748.44   383.8  742.04     394     737
     404  735.88     414  736.19   454.5  739.04   464.6  740.23   474.7   743.1
   484.8  747.43   595.9  798.84   717.1  856.44   747.4  871.38   797.9   897.9
#Mann= 3 , 0 , 0
       0      .1       0     394    .045       0     414      .1       0
Bank Sta=394,414
XS Rating Curve= 0 ,0
Exp/Cntr=0.3,0.1

Type RM Length L Ch R = 1 ,7470.5  ,339.3,350,360.8
XS GIS Cut Line= 3
     1585595.171      393642.052     1585974.045      393486.735
     1586349.195      393322.196
#Sta/Elev= 30
      10  875.19    39.9  858.66    49.9  853.78   109.9  828.07   119.8  824.16
   139.8  817.64   189.8  803.63   209.7  797.04   299.6  763.57   339.6   746.5
   359.5  738.67   369.5  735.27   379.5  732.72   389.5   731.2   399.5   730.5
   409.5  730.64   459.4  732.96   509.4  733.91   539.4  734.98   589.3   737.7
   599.3   738.7   609.3  740.39   629.3  745.36   639.3  748.33   659.3  755.35
   679.2  761.35   739.2  781.05   769.2  792.25   779.2  795.34   819.1  804.11
#Mann= 3 , 0 , 0
       0      .1       0   389.5    .045       0   409.5      .1       0
Bank Sta=389.5,409.5
XS Rating Curve= 0 ,0
Exp/Cntr=0.3,0.1

Type RM Length L Ch R = 1 ,7120.5  ,450.8,457,463.5
XS GIS Cut Line= 3
     1585642.385      393802.211     1586056.402      393816.883
     1586459.554      393826.493
#Sta/Elev= 30
    10.1  887.48     101  841.33   181.9  800.67   212.2  785.16   232.4  774.67
   252.6  763.95   272.8  752.92   303.1  735.93   313.2  730.58   323.3  727.04
   333.4  726.03     384  725.84   404.3  725.44   414.3  725.24   424.3  725.43
   444.5  725.94     505  726.64   515.1  727.85   525.2  731.34   535.3  736.44
   605.8  773.58   615.9  778.54     626  782.86   686.5   806.9   757.1  836.77
   767.1  841.26   777.2  846.05   787.3  851.23   807.5  862.41   817.5  868.32
#Mann= 3 , 0 , 0
    10.1      .1       0   404.3    .045       0   424.3      .1       0
#XS Ineff= 2 , 0
          335.04  756.82
Permanent Ineff=
       F       F
Bank Sta=404.3,424.3
XS Rating Curve= 0 ,0
Exp/Cntr=0.3,0.1

Type RM Length L Ch R = 1 ,6663.5  ,331.9,343,356.3
XS GIS Cut Line= 3
     1585659.876      394128.258     1585954.097       394222.56
     1586384.113      394347.038
#Sta/Elev= 30
      10   860.1    39.9  845.66    69.8  830.61    99.7  814.79   109.6   809.2
   119.6  803.25   129.6  796.87   139.5  790.18   169.4  769.44   179.4  762.07
   189.4  754.13   209.3  737.38   219.3  730.46   229.2  726.35   239.2  725.08
   249.2   724.7   328.9  722.74   368.7  721.29   418.4   718.5   448.2  715.71
   458.2  715.36   468.2     716   478.1  717.99   547.7  738.13   597.5  753.94
   627.3  763.66   657.2  773.77   667.1  776.72   726.8  791.25   756.6  797.91
#Mann= 3 , 0 , 0
       0      .1       0   448.2    .045       0   468.2      .1       0
Bank Sta=448.2,468.2
XS Rating Curve= 0 ,0
Exp/Cntr=0.3,0.1

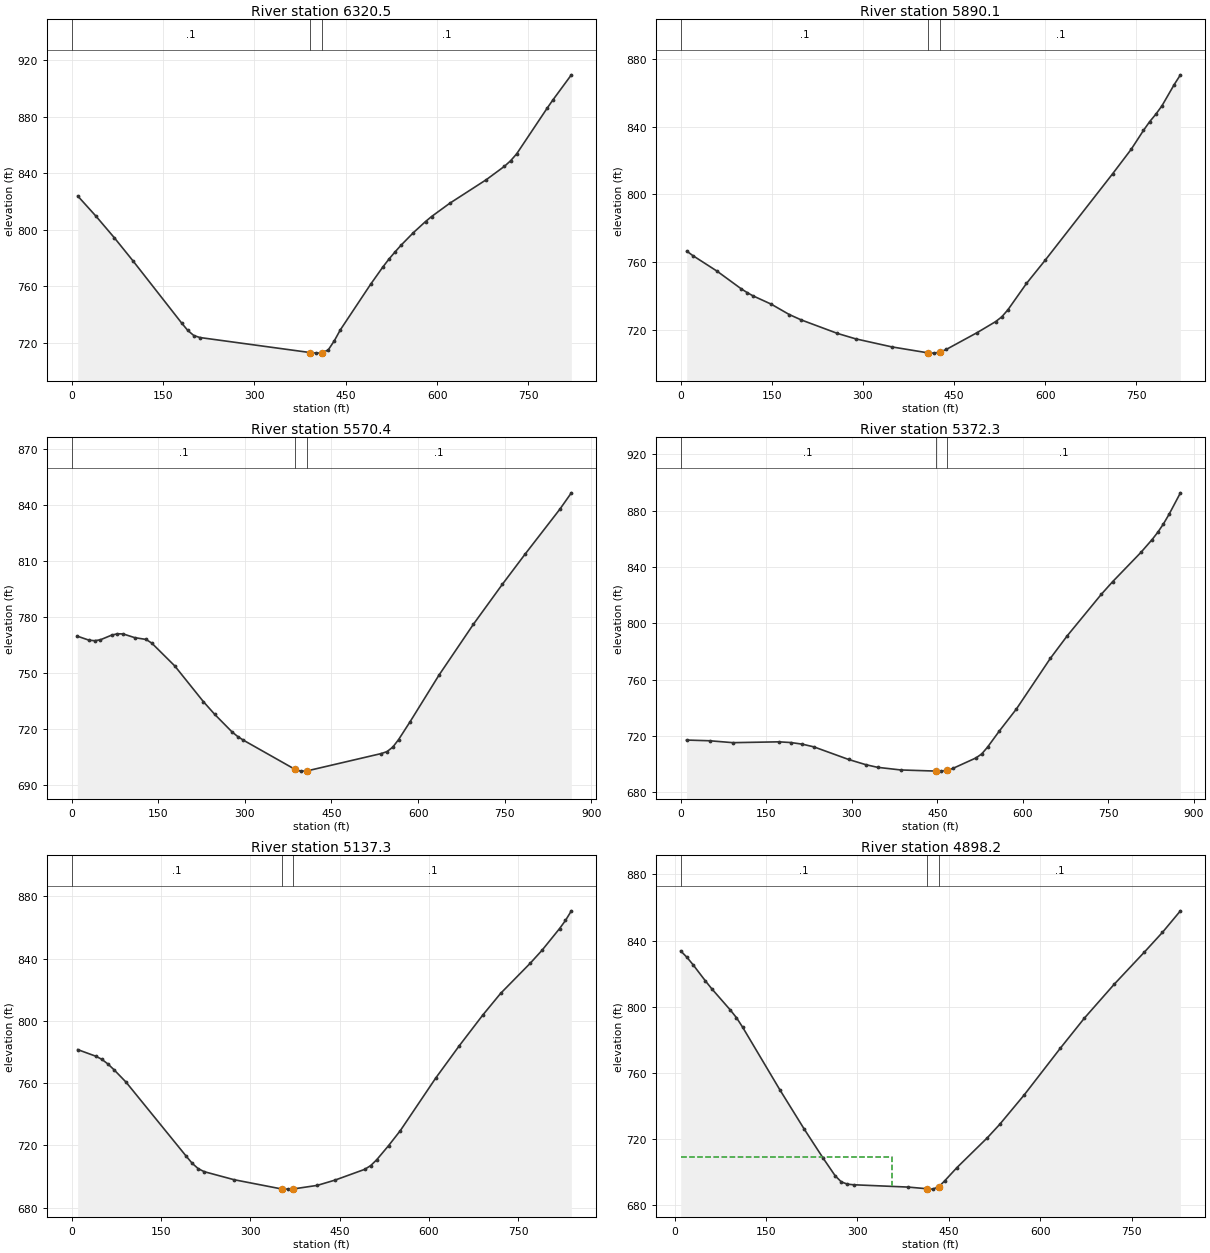
Type RM Length L Ch R = 1 ,6320.5  ,439.9,430.4,417.7
XS GIS Cut Line= 3
     1585601.812      394273.228     1585909.439      394546.223
     1586191.021      394843.111
#Sta/Elev= 30
      10  823.83    40.1  809.45    70.2  794.18   100.3  778.08   180.6   733.8
   190.6  728.58   200.6  724.93   210.7  723.52   391.3  712.89   401.3  712.47
   411.3  712.68   421.3  714.74   431.3  721.24   441.2  728.99   491.1   761.4
   511.1  773.58   521.1  779.18   531.1  784.25     541  789.01     561  797.81
     581  805.71   590.9  809.25   620.9   818.7   680.8  835.38   710.7  844.89
   720.7  848.79   730.7   853.7   780.6  885.99   790.5  892.09   820.5   909.7
#Mann= 3 , 0 , 0
       0      .1       0   391.3    .045       0   411.3      .1       0
Bank Sta=391.3,411.3
XS Rating Curve= 0 ,0
Exp/Cntr=0.3,0.1

Type RM Length L Ch R = 1 ,5890.1  ,327.8,319.7,313
XS GIS Cut Line= 3
     1585275.125      394720.473     1585652.677      394872.653
     1586048.399      394999.606
#Sta/Elev= 30
     9.9  766.66    19.9  764.01    59.6  754.89    99.3  744.52   109.2  742.26
   119.1  740.28   148.9  735.42   178.7   729.3   198.6   726.1   258.1  718.17
   287.9  714.99   347.5  710.25   407.2  706.72   417.2  706.57   427.2  707.18
   437.5   708.8   488.2  718.68   518.6  725.16   528.7  727.98   538.8  732.15
   569.2  747.58   599.7  761.13   711.2  812.24   741.6  826.57   761.8  837.68
     772  842.84   782.1  847.19   792.2  852.15   812.5  864.72   822.7  870.44
#Mann= 3 , 0 , 0
       0      .1       0   407.2    .045       0   427.2      .1       0
Bank Sta=407.2,427.2
XS Rating Curve= 0 ,0
Exp/Cntr=0.3,0.1

Type RM Length L Ch R = 1 ,5570.4  ,186.4,198.2,206.3
XS GIS Cut Line= 3
     1585101.221      395116.419     1585507.756      395127.289
      1585966.09      395148.517
#Sta/Elev= 30
     9.9  769.73    29.8  767.61    39.7  767.29    49.6  767.77    69.4   770.3
    79.4  771.01    89.3  770.92   109.1  768.95   128.9  767.97   138.9  765.97
   178.5   753.8   228.1  734.63     248  727.71   277.7  718.39   287.7  715.87
   297.6   713.9   386.8  698.28   396.8  697.32   406.8  697.38   536.3  706.75
   546.3  707.81   556.3  710.24   566.3  714.27   586.2  723.84   636.1  748.78
   695.9  776.16   745.8  797.48   785.7  813.89   845.6  837.87   865.5  846.64
#Mann= 3 , 0 , 0
       0      .1       0   386.8    .045       0   406.8      .1       0
Bank Sta=386.8,406.8
XS Rating Curve= 0 ,0
Exp/Cntr=0.3,0.1

Type RM Length L Ch R = 1 ,5372.3  ,235.6,235,220.9
XS GIS Cut Line= 4
      1585120.47      395256.106     1585384.515      395256.106
     1585697.597      395342.864     1585984.274      395320.231
#Sta/Elev= 30
    10.2  717.13    50.8  716.63    91.4  715.28   172.6  715.87     193  715.37
   213.3  714.22   233.6  712.29   294.5  703.35     325  699.62   345.3  697.78
   385.9  695.91   446.9  695.12   456.9  695.08   466.9  695.54   477.2  696.97
   517.9  704.45     528  707.31   538.2  712.11   558.5  723.36   588.9  739.23
   648.4  775.14   678.2  791.24   737.7  820.55   757.5  829.48   807.1  850.26
   826.9  859.44   836.8  864.59   846.7  870.52   856.7  877.44   876.5  892.57
#Mann= 3 , 0 , 0
       0      .1       0   446.9    .045       0   466.9      .1       0
Bank Sta=446.9,466.9
XS Rating Curve= 0 ,0
Exp/Cntr=0.3,0.1

Type RM Length L Ch R = 1 ,5137.3  ,240.4,239.1,237.4
XS GIS Cut Line= 4
     1585143.103      395486.202     1585365.655      395474.886
     1585652.332      395388.129     1585969.185      395376.812
#Sta/Elev= 30
    10.1  781.58    40.5  777.34    50.6  775.36    60.8  772.37    70.9  768.74
    91.2  760.75   192.5  713.06   202.6  708.48   212.7  705.05   222.8  703.13
   272.8  697.98   352.6  692.05   362.6  691.93   372.6  692.07   412.5  694.33
   442.5  697.74   492.4  704.66   502.4  707.09   512.4  710.79   532.3  719.85
   552.1  729.53   611.5  763.27   651.2  784.09   690.8  803.87   720.5  817.67
   770.1  836.98   789.9   845.3   819.6  859.34   829.5  864.55   839.4  870.74
#Mann= 3 , 0 , 0
       0      .1       0   352.6    .045       0   372.6      .1       0
Bank Sta=352.6,372.6
XS Rating Curve= 0 ,0
Exp/Cntr=0.3,0.1

Type RM Length L Ch R = 1 ,4898.2  ,244,243.6,243.3
XS GIS Cut Line= 4
     1585185.879      395738.306     1585434.835      395689.269
     1585796.954      395576.107     1585981.785       395508.21
#Sta/Elev= 30
    10.1  833.71    20.3  829.87    30.4  825.36    50.7  815.57    60.9  810.93
    91.3  798.12   101.5  793.44   111.6  787.71   172.5  750.01   213.1  725.91
   243.6  708.67   263.7  697.84   273.7  694.23   283.7  692.87   293.7  692.51
   383.5   691.1   413.5  690.12   423.5  689.87   433.5  691.28   443.4  694.95
   463.4  702.92   513.3  720.93   533.3  728.91   573.2  746.54   633.1  775.03
   672.5  793.17   721.7  813.74     771  833.06   800.5  844.92     830  857.93
#Mann= 3 , 0 , 0
    10.1      .1       0   413.5    .045       0   433.5      .1       0
#XS Ineff= 2 , 0
          357.01  709.39
Permanent Ineff=
       F       F
Bank Sta=413.5,433.5
XS Rating Curve= 0 ,0
Exp/Cntr=0.3,0.1

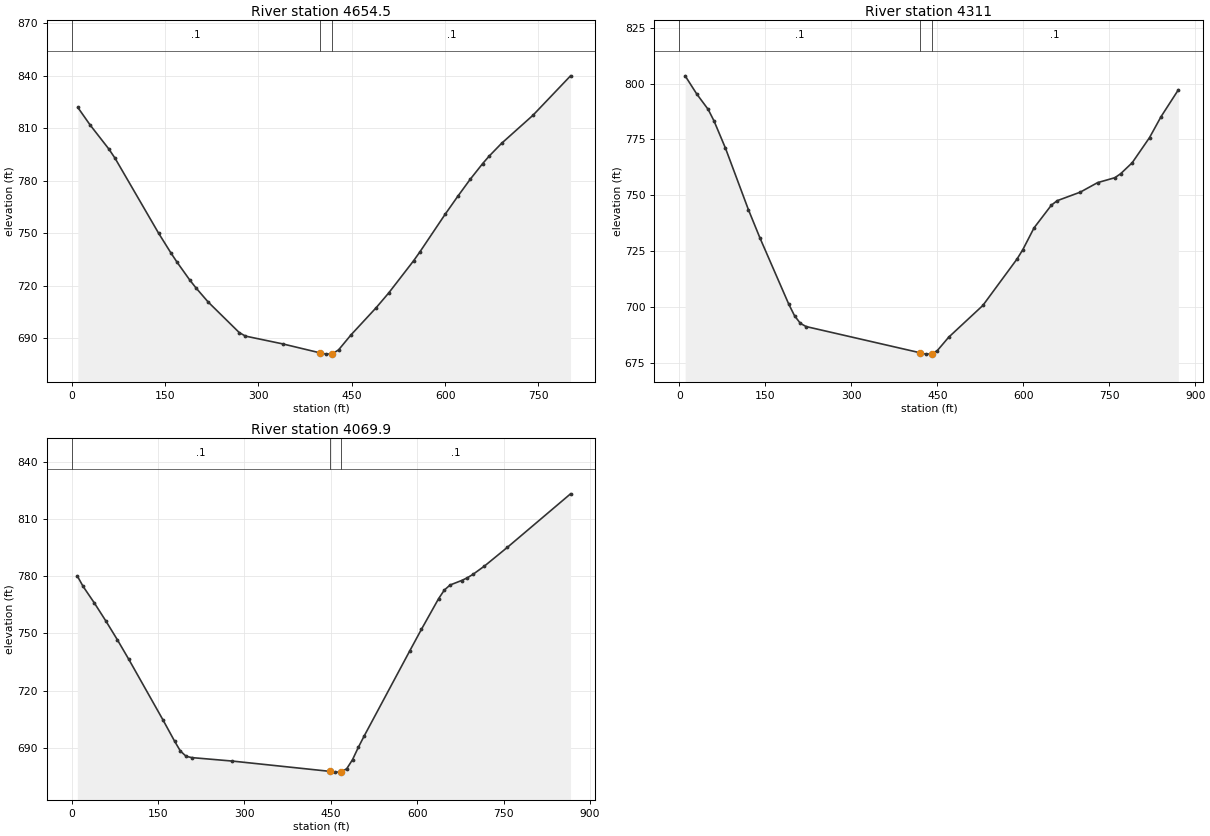
Type RM Length L Ch R = 1 ,4654.5  ,329.4,343.5,357.7
XS GIS Cut Line= 3
     1585282.669      395995.431     1585709.149      395855.513
     1586044.627      395746.475
#Sta/Elev= 30
      10   821.8    29.9  811.72    59.8  798.08    69.8  792.79   139.6  750.06
   159.6  738.66   169.6  733.31   189.5  723.38   199.5  718.85   219.4  710.65
   269.3  693.21   279.3  691.18   339.1  686.73   398.9  681.62   408.9  680.88
   418.9  681.06   428.9   683.3   448.8  691.85   489.2  707.37   509.3  715.76
   549.6  734.29   559.7  739.37     600  760.72   620.2  770.94   640.3  780.73
   660.5  789.79   670.6  793.92   690.7  801.28   741.1  817.31   801.6  839.88
#Mann= 3 , 0 , 0
       0      .1       0   398.9    .045       0   418.9      .1       0
Bank Sta=398.9,418.9
XS Rating Curve= 0 ,0
Exp/Cntr=0.3,0.1

Type RM Length L Ch R = 1 ,4311    ,248.8,241.1,233.3
XS GIS Cut Line= 4
     1585356.661      396191.333     1585610.839      396131.226
     1585957.869      396217.983     1586199.281      396146.314
#Sta/Elev= 30
      10  803.48    30.1  795.41    50.2  788.45    60.3  783.35    80.4  771.09
   120.5  743.54   140.6  730.91   190.9  701.28   200.9  696.15     211  692.76
     221  691.31   420.1  679.57   430.1  678.97   440.1   679.1     450  680.53
   469.9  686.54   529.5  700.74   589.1   721.5     599  725.58   618.9  735.47
   649.1  745.61   659.2  747.61   699.5  751.44   729.7  755.69   759.9   757.9
     770  759.68   790.1  764.58   820.4  775.85   840.5  785.22   870.7  797.22
#Mann= 3 , 0 , 0
       0      .1       0   420.1    .045       0   440.1      .1       0
Bank Sta=420.1,440.1
XS Rating Curve= 0 ,0
Exp/Cntr=0.3,0.1

Type RM Length L Ch R = 1 ,4069.9  ,4048.3,4069.9,4090.5
XS GIS Cut Line= 4
     1585369.427      396334.917     1585516.537      396417.903
     1585954.097      396391.498     1586206.825      396334.917
#Sta/Elev= 30
     9.9  780.12    19.9  774.69    39.7  765.86    59.6  756.45    79.5  746.61
    99.4  736.31     159  704.36   178.9  693.35   188.8  688.26   198.8  685.47
   208.8  684.78   278.5  682.98   447.8  677.58   457.8  677.16   467.8  677.21
   477.7  678.98   487.7  683.71   497.7  690.13   507.6  695.95   587.3  740.96
   607.3  752.13   637.1  768.22   647.1  772.75   657.1  775.41     677  777.75
   686.9  779.17   696.9  781.01   716.8  785.36   756.7  795.22   866.2  823.27
#Mann= 3 , 0 , 0
       0      .1       0   447.8    .045       0   467.8      .1       0
Bank Sta=447.8,467.8
XS Rating Curve= 0 ,0
Exp/Cntr=0.3,0.1

Chan Stop Cuts=-1
Use User Specified Reach Order=0